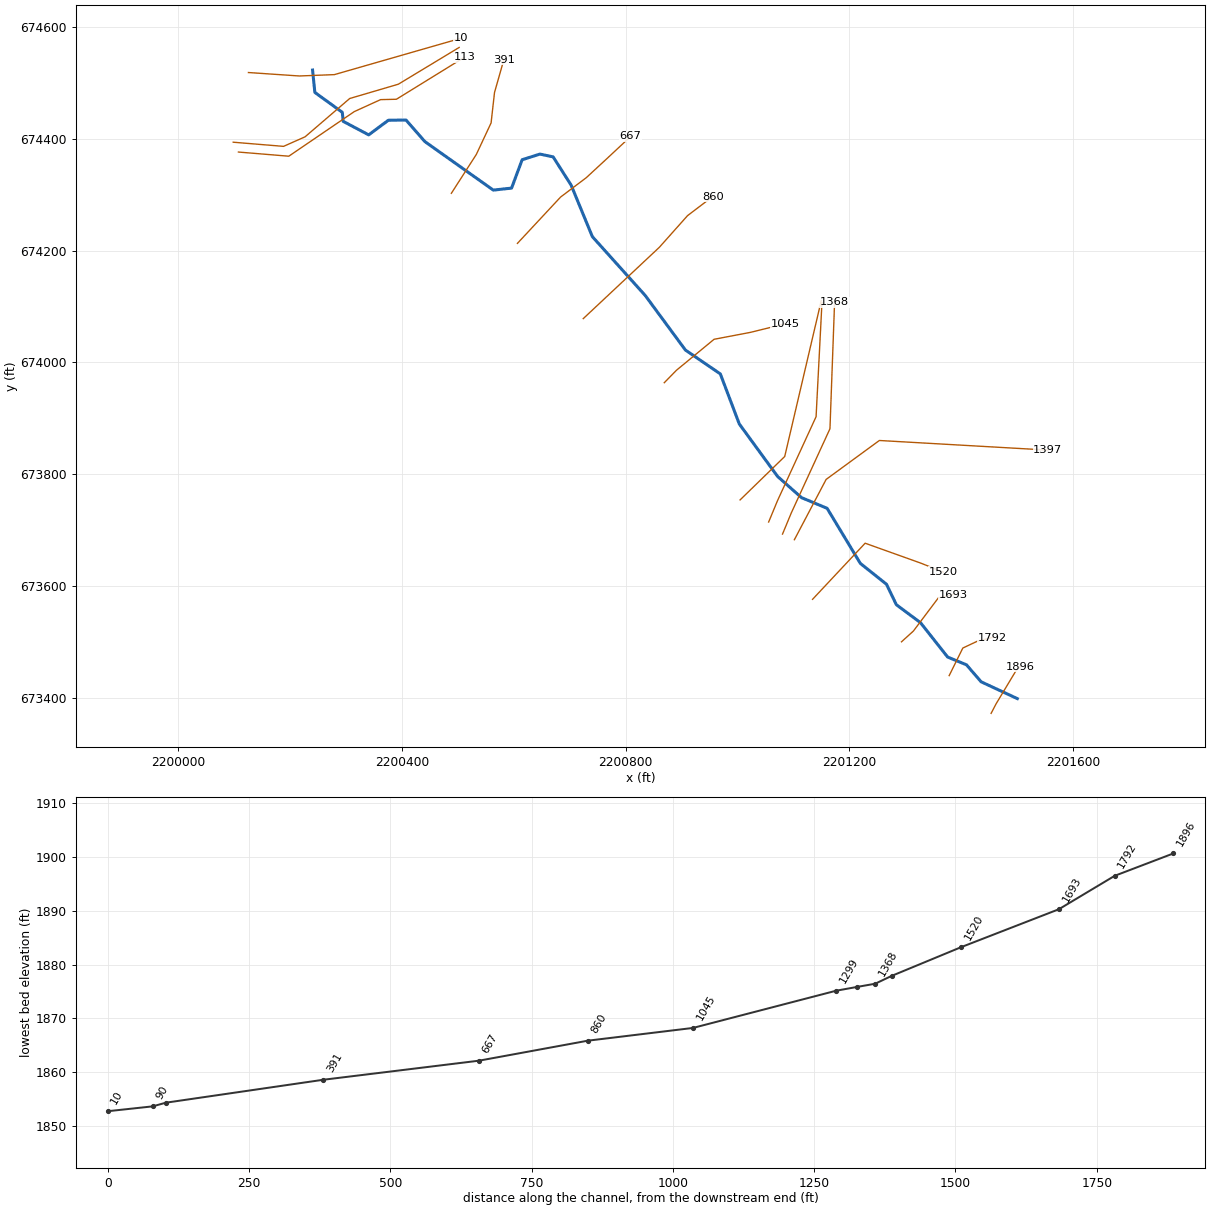
--- RFTENMILT1.prj (project) ---

Proj Title=RFTENMILT1
Current Plan=p01
Default Exp/Contr=0,0
English Units
Geom File=g01
Flow File=f01
Plan File=p01
BEGIN DESCRIPTION:
---------- MODELED AS PART OF WVEMD CTP PROGRAM, 2023----------
Stream Name: Right Fork Tenmile Creek Tributary 1
Flood Zone:  AFH
Upshur County, WV
HEC-RAS Version: RAS 6.3
Vertical Datum: NAVD88
Projection: NAD 1983 StatePlane West Virginia S FIPS 4702 (US Feet)
Terrain: 1-meter LIDAR (FEMA Region III 3DEP collected 2016-2018)
Land Use: 2019 NLCD
Hydrologic Method:
WV SIR2010-5033 regression equations
Additional Model Notes:
Coincident peak with Right Fork Ten Mile Creek.  KWSE boundary condition used.
END DESCRIPTION:
DSS Export Rating Curves= 0
DSS Export Rating Curve Sorted= 0
DSS Export Volume Flow Curves= 0
DXF OffsetX= 0
DXF OffsetY= 0
DXF ScaleX= 0
DXF ScaleY= 0

--- RFTENMILT1.p01 (plan) ---

Plan Title=Floodplain
Program Version=6.30
Short Identifier=Floodplain
Geom File=g01
Flow File=f01
Subcritical Flow
K Sum by GR= 0
Std Step Tol= 0.01
Critical Tol= 0.01
Num of Std Step Trials= 20
Max Error Tol= 0.3
Flow Tol Ratio= 0.001
Split Flow NTrial= 30
Split Flow Tol= 0.02
Split Flow Ratio= 0.02
Log Output Level= 0
Friction Slope Method= 1
Unsteady Friction Slope Method= 2
Unsteady Bridges Friction Slope Method= 1
Parabolic Critical Depth
Global Vel Dist= 0 , 0 , 0
Global Log Level= 0
CheckData=False
Encroach Param=-1 ,0,0, 0
Mapping Interval=1HOUR
Computation Time Step Use Courant=        0
Computation Time Step Use Time Series=    0
Computation Time Step Count To Double=0
Computation Time Step Max Doubling=0
Computation Time Step Max Halving=0
Computation Time Step Residence Courant=0
Run HTab= 0
Run UNet= 0
Run Sediment= 0
Run PostProcess= 0
Run WQNet= 0
Run RASMapper=-1
UNET Theta= 0
UNET Theta Warmup= 0
UNET ZTol= 0
UNET ZSATol= 0
UNET MxIter= 0
UNET Max Iter WO Improvement= 0
UNET MaxInSteps= 0
UNET DtIC= 0
UNET DtMin= 0
UNET MaxCRTS= 0
UNET WFStab= 0
UNET SFStab= 0
UNET WFX= 1
UNET SFX= 1
UNET Gravity=32.17405
UNET 1D Methodology=Finite Difference
UNET DSS MLevel= 1
UNET Pardiso=0
UNET DZMax Abort= 0
UNET Use Existing IB Tables= 0
UNET Froude Reduction=False
UNET Froude Limit= 0
UNET Froude Power= 0
UNET D1 Cores= 0
UNET WindReference=Eulerian
UNET WindDragFormulation=Hsu (1988)
UNET D2 Coriolis=0
UNET D2 Cores= 0
UNET D2 Theta= 1
UNET D2 Theta Warmup= 1
UNET D2 Z Tol= 0.01
UNET D2 Volume Tol= 0.01
UNET D2 Max Iterations= 20
UNET D2 Equation= 0
UNET D2 RampUpFraction=0.1
UNET D2 TimeSlices= 1
UNET D2 Turbulence Formulation=Non-Conservative (original)
UNET D2 Eddy Viscosity=0.3
UNET D2 Transverse Eddy Viscosity=0.1
UNET D2 Smagorinsky Mixing=0
UNET D2 BCVolumeCheck=0
UNET D2 Cores=0
UNET D2 SolverType=PARDISO (Direct)
UNET D2 Minimum Iterations= 3
UNET D2 Maximum Iterations= 30
UNET D2 Restart Number= 10
UNET D2 Relaxation Coeff=1.3
UNET D2 SOR Precondition Iterations= 10
UNET D2 ILUT Maximum Fill= 8
UNET D2 ILUT Tolerance=1E-08
UNET D2 Convergence Tolerance=0.00001
UNET D1D2 MaxIter= 0
UNET D1D2 ZTol=0.01
UNET D1D2 QTol=0.1
UNET D1D2 MinQTol=1
Write IC File= 0
Write IC File at Fixed DateTime=0
Write IC File at Sim End=0
Echo Input=False
Echo Parameters=False
Echo Output=False
Write Detailed= 0
HDF Write Warmup=0
HDF Write Time Slices=0
HDF Flush=0
HDF Compression= 1
HDF Chunk Size= 1
HDF Spatial Parts= 1
HDF Use Max Rows=0
HDF Fixed Rows= 1
Calibration Method= 0
Calibration Iterations= 20
Calibration Max Change=0.05
Calibration Tolerance=0.2
Calibration Maximum=1.5
Calibration Minimum=0.5
Calibration Optimization Method= 1
WQ AD Non Conservative
WQ ULTIMATE=-1
WQ Max Comp Step=1HOUR
WQ Output Interval=15MIN
WQ Output Selected Increments= 0
WQ Output face flow=0
WQ Output face velocity=0
WQ Output face area=0
WQ Output face dispersion=0
WQ Output cell volume=0
WQ Output cell surface area=0
WQ Output cell continuity=0
WQ Output cumulative cell continuity=0
WQ Output face conc=0
WQ Output face dconc_dx=0
WQ Output face courant=0
WQ Output face peclet=0
WQ Output face adv mass=0
WQ Output face disp mass=0
WQ Output cell mass=0
WQ Output cell source sink temp=0
WQ Output nsm pathways=0
WQ Output nsm derived pathways=0
WQ Create Restart=0
WQ Fixed Restart=0
WQ System Summary=0
WQ Write To DSS=0
Sorting and Armoring Iterations= 10
XS Update Threshold= 0.02
Bed Roughness Predictor= 0
Hydraulics Update Threshold= 0.02
Energy Slope Method= 1
Volume Change Method= 1
Sediment Retention Method= 0
Sediment TS Multiplier= 1
Warm Up Method= 0
XS Weighting Method= 0
Number of US Weighted Cross Sections= 1
Number of DS Weighted Cross Sections= 1
Upstream XS Weight=0
Main XS Weight=1
Downstream XS Weight=0
Number of DS XS's Weighted with US Boundary= 1
Upstream Boundary Weight= 1
Weight of XSs Associated with US Boundary= 0
Number of US XS's Weighted with DS Boundary= 1
Downstream Boundary Weight= 0.5
Weight of XSs Associated with DS Boundary= 0.5
Percentile Method= 0
Sediment Output Level= 3
Mass or Volume Output= 0
Output Increment Type= 1
Profile and TS Output Increment= 1
Transport Output Increment 1
XS Output Flag= 0
XS Output Increment= 10
Read HDF5 Sediment Hotstart= 0
Sediment Hotstart Type= 0
Write Gradation File= 0
Read Gradation Hotstart= 0
Write HDF5 File= 1
Write Binary Output= 1
Write DSS Sediment File= 0
DSS Sediment Output Type= 1
SV Curve= 0
Specific Gage Flag= 0
Subcell Erosion Methods= 0
Subcell Deposition Methods= 0
Advection Scheme= 1
Matrix Solver= 0
Implicit Weighting Factor= 1
Maximum Outer Loop Convergence Iterations= 5
Convergence Maximum Absolute= 0.001
Convergence RMSE= 0.0001
Grain Fractions Max Abs Error= 0.001
Max Subgrid Regions= 1
Max Subgrid Length Scale= 3.402823E+38
Initial Layer Thickness= 3.402823E+38
Min Layer Thickness= 3.402823E+38
Max Layer Thickness= 3.402823E+38
Number of Layers= 5

--- RFTENMILT1.f01 (steady flow) ---

Flow Title=Flows
Program Version=6.31
Number of Profiles= 1
Profile Names=01pct
River Rch & RM=RFTENMILT1,Main            ,1896
     458
River Rch & RM=RFTENMILT1,Main            ,113
     739
Boundary for River Rch & Prof#=RFTENMILT1,Main            , 1
Up Type= 0
Dn Type= 1
Dn Known WS=1855.3
DSS Import GetInterval= 0
DSS Import GetPeak= 0
DSS Import FillOption= 0

--- RFTENMILT1.g01 (geometry) ---

Geom Title=Geometry
Program Version=6.31

River Reach=RFTENMILT1      ,Main
Reach XY= 30
2201500.20800002673398.8880000112201435.33400004673429.021000013
2201409.23600003673459.3540000022201375.52600002673473.261000007
2201327.07353495673534.6308384982201283.89600003673566.780000001
     2201266.211673603.4089999942201219.45200001673640.695999995
2201160.04500003673739.1940000212201114.28699999673758.281000018
     2201071.506673796.1400000012201003.05500001673889.916000009
2200969.14500004673979.4570000172200906.61800003674022.238000005
2200834.87699999674119.648000017     2200740.271674224.985000014
     2200702.354674317.0160000182200670.13200001674367.609000012
2200646.55200003674372.6170000142200614.73100004674362.487000003
2200595.78699999674311.7500000152200563.13500001674308.173000008
2200440.74300002674394.9670000082200407.06200001674433.513000011
2200375.46900001674433.0840000062200340.30000004674406.957000017
     2200294.685674431.1659999942200293.11100005674447.278000012
2200244.03399999674482.8760000022200239.95697646674522.825546473

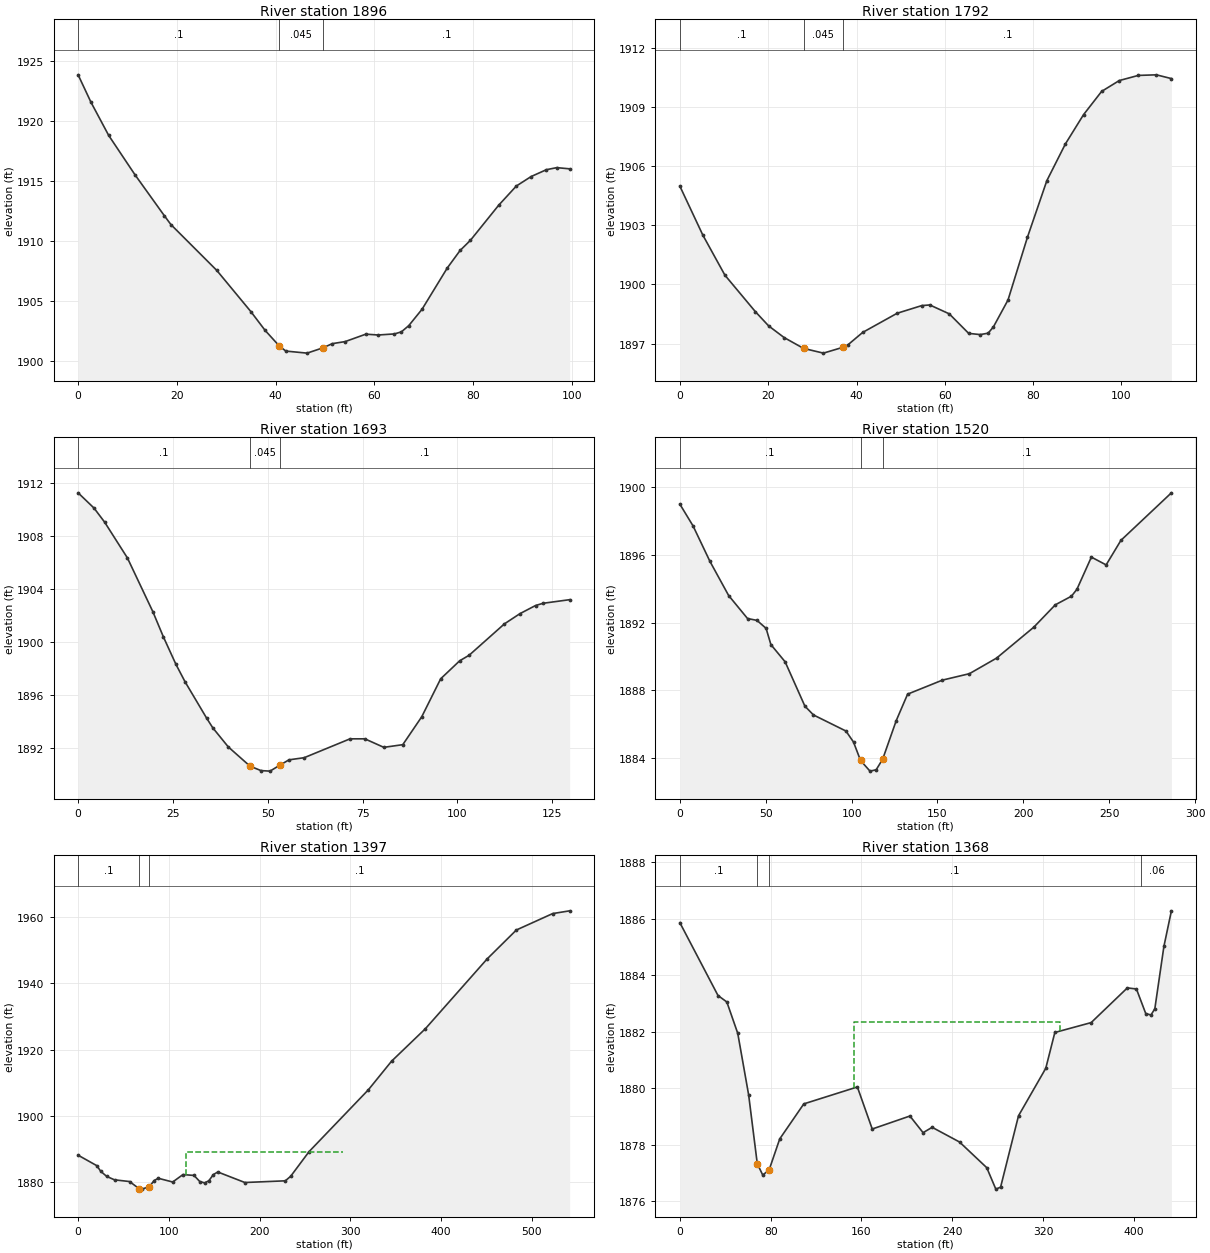
Type RM Length L Ch R = 1 ,1896    ,103.9,103.9,103.9
XS GIS Cut Line= 4
2201453.29550679673372.5030700892201462.17708179673389.526088841
2201498.44351305 673449.846785722201506.21489117673456.137901345
#Sta/Elev= 30
       0 1923.87     2.6 1921.59     6.2 1918.82    11.5 1915.56    17.5 1912.12
    18.8  1911.4    28.1 1907.58      35 1904.15    37.9 1902.58    40.8 1901.27
    42.1 1900.86    46.4 1900.69    49.6 1901.13    51.5 1901.48    54.1 1901.65
    58.3 1902.27    60.8  1902.2    64.1 1902.29    65.5 1902.46      67 1902.98
    69.7 1904.35    74.8 1907.78    77.4 1909.24    79.5 1910.09    85.2    1913
    88.8 1914.61    91.8  1915.4    94.9 1915.97      97 1916.14    99.6 1916.04
#Mann= 3 ,-1,0
       0      .1       0    40.8    .045       0    49.6      .1       0
Bank Sta=40.8,49.6
XS Rating Curve= 0 ,0
Exp/Cntr(USF)=0,0
Exp/Cntr=0.3,0.1

Type RM Length L Ch R = 1 ,1792    ,99.7,98.9,95.6
XS GIS Cut Line= 4
2201378.33513562673440.0570524162201402.70159653673489.297608832
2201429.60623044673501.9884738882201455.49559516673508.080089115
#Sta/Elev= 29
       0 1904.98     5.2  1902.5    10.2 1900.47    17.1 1898.62    20.1  1897.9
    23.6 1897.31      28 1896.76    32.5 1896.52      37 1896.82      38 1896.93
    41.4 1897.57    49.2 1898.54    54.8 1898.93    56.6 1898.96      61 1898.51
    65.4 1897.52      68 1897.46    69.8 1897.53      71 1897.85    74.3 1899.21
    78.7 1902.39    83.1 1905.26    87.3 1907.12    91.4  1908.6    95.5 1909.78
    99.5 1910.33   103.8 1910.59   107.9 1910.62   111.3 1910.43
#Mann= 3 ,-1,0
       0      .1       0      28    .045       0      37      .1       0
Bank Sta=28,37
XS Rating Curve= 0 ,0
Exp/Cntr(USF)=0,0
Exp/Cntr=0.3,0.1

Type RM Length L Ch R = 1 ,1693    ,173.2,172.9,171.6
XS GIS Cut Line= 4
2201293.05252244673500.4655700812201314.37317574673519.755684966
2201359.04502073673579.1489334272201384.93438545673584.732914052
#Sta/Elev= 30
       0 1911.23     4.2 1910.08       7 1909.02      13 1906.33    19.7 1902.29
    22.5 1900.38    25.8 1898.32    28.2 1897.01    33.9 1894.27    35.5 1893.55
    39.6 1892.11    45.3 1890.67    48.2 1890.33    50.6 1890.29    53.2 1890.74
    55.6 1891.14    59.6  1891.3    71.7 1892.72    75.6 1892.72    80.6 1892.08
    85.6 1892.28    90.6 1894.38    95.6 1897.24   100.6 1898.59   103.1 1899.01
   112.4 1901.37   116.5 1902.14   120.6 1902.75   122.6 1902.92   129.6 1903.19
#Mann= 3 ,-1,0
       0      .1       0    45.3    .045       0    53.2      .1       0
Bank Sta=45.3,53.2
XS Rating Curve= 0 ,0
Exp/Cntr(USF)=0,0
Exp/Cntr=0.3,0.1

Type RM Length L Ch R = 1 ,1520    ,119.5,122.9,124.7
XS GIS Cut Line= 4
2201134.02569461673576.4333961172201228.04430451673676.778130017
2201328.02357223673641.0077332092201367.50626351673625.214656695
#Sta/Elev= 30
       0 1899.01     7.7 1897.72    17.5 1895.63    28.4 1893.61    39.4 1892.25
    44.9 1892.14    50.2 1891.67      53 1890.71    61.3 1889.69    72.8 1887.07
    77.8 1886.55    96.7  1885.6   101.1 1884.95   105.2 1883.86   110.7 1883.23
   114.3 1883.31   118.1 1883.94     126 1886.22   132.6 1887.78   152.9 1888.61
   168.6 1888.99   184.4 1889.91   206.1 1891.74   218.6 1893.06     228 1893.57
   231.2 1893.98   239.6 1895.88   248.2 1895.42   256.8 1896.87   286.2 1899.68
#Mann= 3 ,-1,0
       0      .1       0   105.2    .045       0   118.1      .1       0
Bank Sta=105.2,118.1
XS Rating Curve= 0 ,0
Exp/Cntr(USF)=0,0
Exp/Cntr=0.3,0.1

Type RM Length L Ch R = 1 ,1397    ,28.5,29.2,29.9
XS GIS Cut Line= 4
2201101.50936146673683.0262889692201158.30629167673790.868561509
2201253.48369244673860.4712072152201554.80795745673843.282334009
#Sta/Elev= 30
       0 1888.13    20.5 1884.98      25 1883.25    31.5 1881.72    40.1 1880.69
    56.7 1880.17    67.2 1878.02    70.2 1877.88    78.51878.629    83.8 1880.47
    88.3 1881.16   104.2 1880.03   115.5 1882.27   127.7 1882.02   134.1 1880.16
   139.4 1879.77     144  1880.4     149 1882.27   153.9 1883.06   183.7 1879.88
   228.3 1880.39   234.2 1881.76   254.5 1889.22   319.9 1907.91   345.4 1916.53
   382.7 1926.35   450.8 1947.45   482.9 1956.15   522.9 1961.11   541.6 1961.94
#Mann= 3 ,-1,0
       0      .1       0    67.2    .045       0    78.5      .1       0
#XS Ineff= 1 ,-1
  118.48   292.1 1888.96
Permanent Ineff=
       F
Bank Sta=67.2,78.5
XS Rating Curve= 0 ,0
Exp/Cntr(USF)=0,0
Exp/Cntr=0.3,0.1

Type RM Length L Ch R = 1 ,1368    ,32.8,32.9,32.8
XS GIS Cut Line= 4
 2201080.3003812673693.0915677392201096.11724783 673731.19583737
2201165.13630226673881.4560704422201173.41659269674107.824626644
#Sta/Elev= 30
       0 1885.86    33.6 1883.28    41.4 1883.05      51 1881.94    60.6 1879.76
    68.21877.324      73 1876.92    78.61877.096      88  1878.2   109.2 1879.44
   156.4 1880.04   169.5 1878.55   202.7 1879.01   214.3 1878.42   222.3 1878.61
   246.4 1878.09   270.4 1877.18   278.4 1876.42   282.6 1876.49   298.4 1879.02
   322.4  1880.7   330.4 1881.97   362.4 1882.32   394.3 1883.55   402.3 1883.51
   410.5 1882.64   415.1 1882.59   418.5 1882.81   426.5 1885.02   433.1 1886.28
#Mann= 4 ,-1,0
       0      .1       0    68.2    .045       0    78.6      .1       0
  406.61     .06       0
#XS Ineff= 1 ,-1
   153.8     335 1882.33
Permanent Ineff=
       F
Bank Sta=68.2,78.6
XS Rating Curve= 0 ,0
Exp/Cntr(USF)=0,0
Exp/Cntr=0.3,0.1

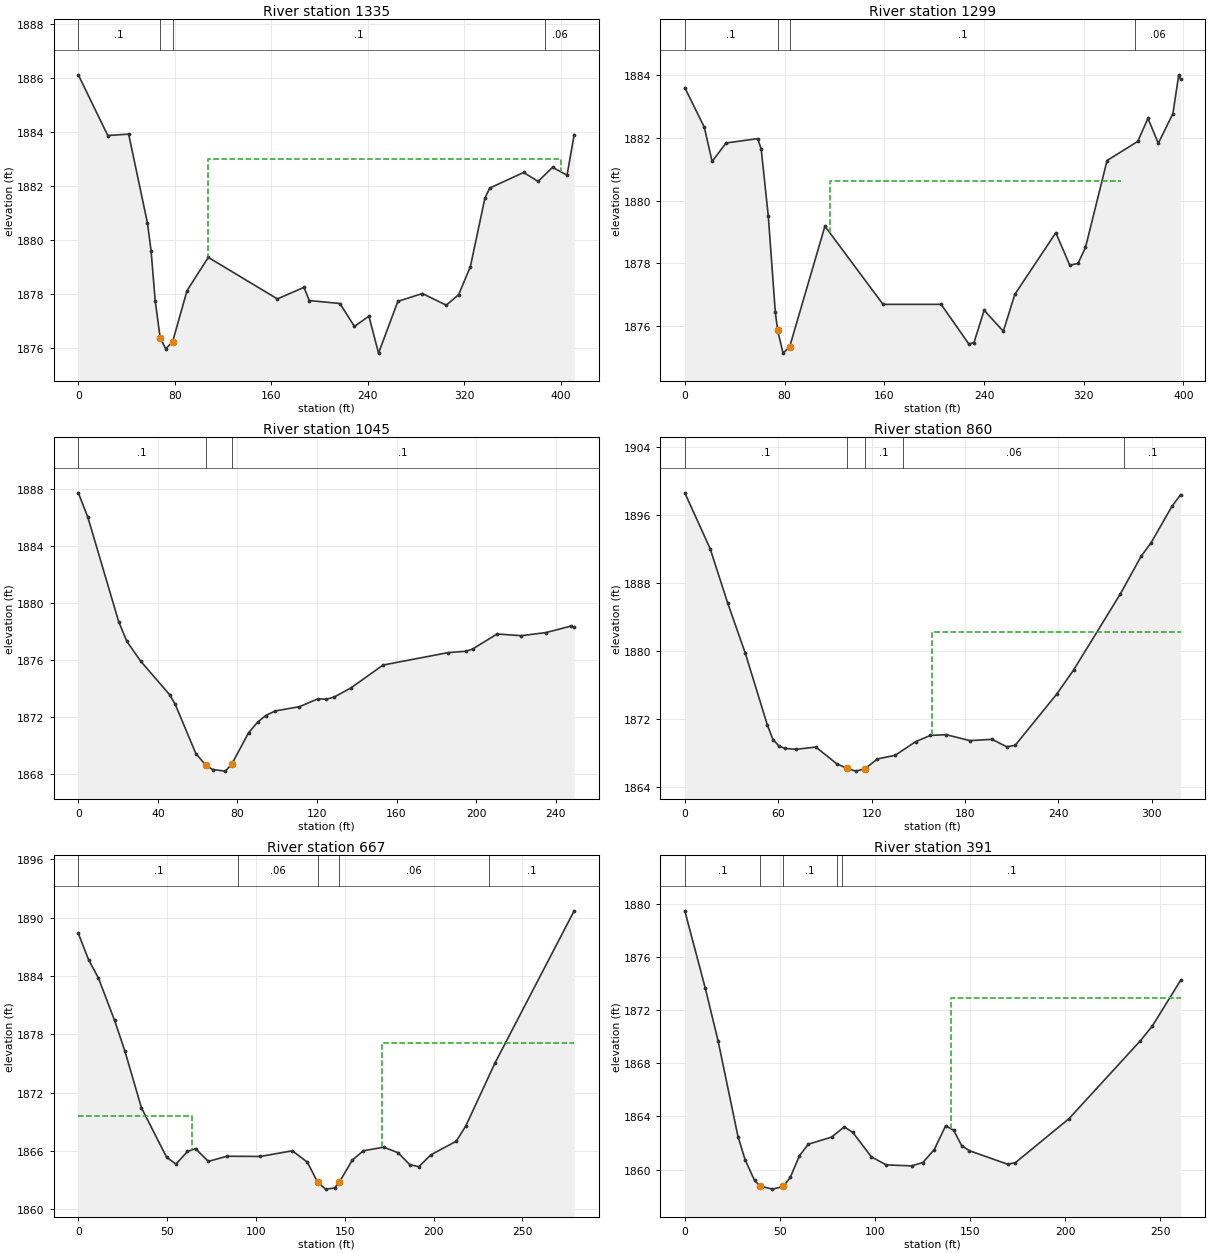
Type RM Length L Ch R = 1 ,1335    ,40.3,36.1,32.8
XS GIS Cut Line= 4
2201055.49665851673714.6600222472201071.31352515673752.764291878
2201140.33257958673903.0245249512201150.84558673674107.003066088
#Sta/Elev= 30
       0 1886.13    24.4 1883.88    41.7 1883.93    57.3 1880.63    60.3  1879.6
    63.7 1877.75    67.81876.387    72.4 1875.97    78.11876.226    90.1 1878.13
   107.7 1879.36     165 1877.82     187 1878.25   191.4 1877.76   216.8 1877.65
   228.8  1876.8   240.8 1877.18   248.8 1875.81   264.8 1877.73   285.1 1878.02
   304.9 1877.59   315.2 1877.98   324.9 1879.02   336.9 1881.55   340.9 1881.93
     369 1882.51     381 1882.18     393  1882.7     405 1882.41   410.9 1883.91
#Mann= 4 ,-1,0
       0      .1       0    67.8    .045       0    78.1      .1       0
  386.61     .06       0
#XS Ineff= 1 ,-1
  107.07     400    1883
Permanent Ineff=
       F
Bank Sta=67.8,78.1
XS Rating Curve= 0 ,0
Exp/Cntr(USF)=0,0
Exp/Cntr=0.3,0.1

Type RM Length L Ch R = 1 ,1299    ,253.3,253.3,252.6
XS GIS Cut Line= 3
2201004.45131618673754.2021888452201084.25459786673831.848625074
2201149.59396523674110.700214242
#Sta/Elev= 30
       0 1883.61    15.7 1882.34    21.9 1881.25    33.1 1881.84    58.5 1881.98
    61.3 1881.64      67 1879.49    72.6 1876.43    74.51875.845    78.8 1875.12
    84.11875.322   112.4 1879.18     159 1876.68   205.6 1876.68   227.7 1875.42
   231.9 1875.45   240.1 1876.49   255.5 1875.82   264.7    1877   297.6 1878.97
   308.8 1877.93   315.4 1877.99   321.4  1878.5   338.7 1881.28   363.3 1881.89
   371.5 1882.63   379.8 1881.83   391.5 1882.78   396.2 1884.02   397.7 1883.88
#Mann= 4 ,-1,0
       0      .1       0    74.5    .045       0    84.1      .1       0
  361.34     .06       0
#XS Ineff= 1 ,-1
  116.34     350 1880.64
Permanent Ineff=
       F
Bank Sta=74.5,84.1
XS Rating Curve= 0 ,0
Exp/Cntr(USF)=0,0
Exp/Cntr=0.3,0.1

Type RM Length L Ch R = 1 ,1045    ,184.9,185.8,186.5
XS GIS Cut Line= 5
 2200868.8425952673963.7636186432200890.77241002673986.150304601
 2200957.9324679674041.4317127842201022.80817006674053.767233619
2201085.85638766674069.300852447
#Sta/Elev= 30
       0 1887.71     4.8 1885.99    20.3 1878.67    24.4 1877.29    31.3 1875.91
    45.9 1873.55    48.7 1872.88    59.1 1869.42    64.2 1868.59    67.6  1868.3
    73.9 1868.19    77.1 1868.67    85.6 1870.88    90.1 1871.62    94.2 1872.09
      99 1872.41   111.2 1872.71   120.6 1873.27   124.7 1873.23   128.7 1873.39
   137.1 1874.03   153.2 1875.63   185.8  1876.5   194.9  1876.6   198.2 1876.75
   210.5 1877.81   222.8 1877.69   235.2 1877.91   247.6 1878.36   249.3 1878.27
#Mann= 3 ,-1,0
       0      .1       0    64.2    .045       0    77.1      .1       0
Bank Sta=64.2,77.1
XS Rating Curve= 0 ,0
Exp/Cntr(USF)=0,0
Exp/Cntr=0.3,0.1

Type RM Length L Ch R = 1 ,860     ,193.6,193,191.2
XS GIS Cut Line= 4
2200723.99238058674078.3687203632200860.16627174674206.031743329
2200910.45776564674262.512959551 2200955.3332525674296.556432342
#Sta/Elev= 30
       0 1898.64    16.3 1892.05    27.5 1885.68    38.9 1879.71    53.1 1871.23
    56.7 1869.53    60.6 1868.77    64.4  1868.5    71.5 1868.39    84.2 1868.66
    97.7 1866.68   104.4 1866.14   109.9 1865.82   115.91866.118   123.8 1867.26
   135.1 1867.68   148.3 1869.29   157.8 1870.03   167.9 1870.12   183.2 1869.42
   197.4 1869.57   206.9 1868.69   212.3 1868.87   239.1 1874.93   249.8 1877.74
   279.9 1886.73   293.2 1891.15   299.7 1892.78     313 1897.04   318.6 1898.43
#Mann= 5 ,-1,0
       0      .1       0   104.4    .045       0   115.9      .1       0
     140     .06       0  282.28      .1       0
#XS Ineff= 2 , 0
                          159.13         1882.24
Permanent Ineff=
       F       F
Bank Sta=104.4,115.9
XS Rating Curve= 0 ,0
Exp/Cntr(USF)=0,0
Exp/Cntr=0.3,0.1

Type RM Length L Ch R = 1 ,667     ,272.2,275.3,279.8
XS GIS Cut Line= 5
2200606.28088368674212.9255465692200683.55415091674295.839198267
2200729.24126511 674330.245543532200766.46780261674364.651888792
2200808.77068613674404.134580077
#Sta/Elev= 30
       0 1888.37     5.8 1885.65    11.3 1883.79    20.4 1879.43    26.2 1876.29
    35.5 1870.46    49.7 1865.36      55 1864.66    61.4 1865.96      66 1866.25
    73.2 1864.94    83.6 1865.47   102.5 1865.45   120.5 1866.03   128.9 1864.86
   134.7 1862.81   139.2 1862.09   144.2  1862.2   146.91862.801   154.2 1865.07
   160.4 1866.03   171.9  1866.4     180 1865.83   186.6  1864.6   191.7  1864.4
   198.4 1865.61   212.7 1867.01   218.1 1868.58   234.5 1875.04   279.1 1890.69
#Mann= 5 ,-1,0
       0      .1       0      90     .06       0   134.7    .045       0
   146.9     .06       0  231.22      .1       0
#XS Ineff= 2 , 0
           64.06 1869.56  171.04         1877.06
Permanent Ineff=
       F       F
Bank Sta=134.7,146.9
XS Rating Curve= 0 ,0
Exp/Cntr(USF)=0,0
Exp/Cntr=0.3,0.1

Type RM Length L Ch R = 1 ,391     ,278.6,278.6,278.6
XS GIS Cut Line= 5
2200488.14075329674302.4754584332200532.81259828674372.021398939
 2200559.2095976674428.3688397872200565.30121283674482.685742225
 2200582.0531547674541.571356084
#Sta/Elev= 30
       0 1879.46    10.7 1873.69    17.5 1869.69      28 1862.48    31.7 1860.76
    36.7 1859.19    39.6 1858.78      46 1858.54    51.9 1858.74    55.5 1859.43
    60.3 1861.05      65 1861.92    77.2 1862.45    83.9 1863.22    88.4  1862.8
    98.1 1860.97     106 1860.36   119.3 1860.29   125.2 1860.54   131.2 1861.51
   137.2  1863.3   141.4 1862.97   145.7 1861.79   149.7 1861.43   169.8 1860.41
   173.9 1860.53   202.1 1863.84   239.6 1869.69     246 1870.82   260.8 1874.24
#Mann= 5 ,-1,0
       0      .1       0    39.6    .045       0    51.9      .1       0
      80     .06       0   82.66      .1       0
#XS Ineff= 1 ,-1
     140 260.761 1872.87
Permanent Ineff=
       F
Bank Sta=39.6,51.9
XS Rating Curve= 0 ,0
Exp/Cntr(USF)=0,0
Exp/Cntr=0.3,0.1

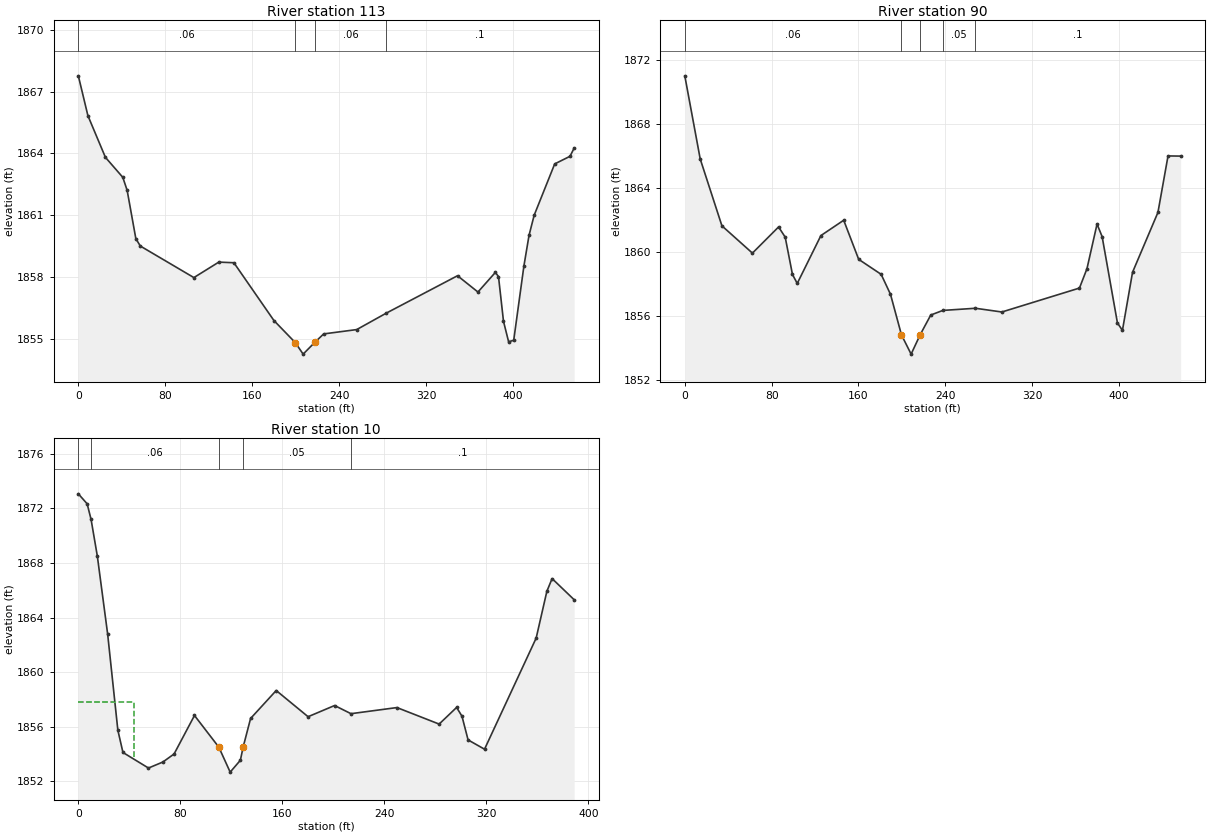
Type RM Length L Ch R = 1 ,113     ,23,23,23
XS GIS Cut Line= 6
2200107.40666158674376.2426109042200197.44969798674368.808719261
2200314.54806868674448.5541890492200361.60800724674469.988848381
2200389.86661105674470.6293118332200511.43607009674545.690772483
#Sta/Elev= 30
       0 1867.76     8.8 1865.83    24.9 1863.81    40.9 1862.84    44.9 1862.21
    52.9 1859.87      57 1859.51   106.3 1857.98   129.2 1858.73   143.1  1858.7
   179.9  1855.9  199.55 1854.83   206.8 1854.27   217.5 1854.84   225.7 1855.25
   256.1 1855.46  283.241856.256   348.8 1858.07   367.6 1857.28   383.6 1858.23
   386.5 1858.03   391.1 1855.86   395.8 1854.87   400.5 1854.94   409.9 1858.55
   414.6 1860.03   419.3    1861   438.2 1863.49   452.3 1863.86   456.1 1864.26
#Mann= 4 ,-1,0
       0     .06       0  199.55    .045       0   217.5     .06       0
  283.24      .1       0
Bank Sta=199.55,217.5
XS Rating Curve= 0 ,0
Exp/Cntr=0.3,0.1

Type RM Length L Ch R = 1 ,90      ,79.9,79.9,79.9
XS GIS Cut Line= 6
2200098.05385143674393.8331852752200188.09688783674386.399293631
2200226.60193621674403.5035510812200306.36248608674471.980901216
2200393.35330405674497.5577066772200502.08325993674563.281346853
#Sta/Elev= 30
       0 1871.03    14.2 1865.82    34.2 1861.63    62.3 1859.92    86.4 1861.56
    92.5 1860.92    99.2 1858.58   103.6 1858.02   125.4 1861.02   146.4 1861.98
   160.2 1859.53   180.9 1858.59   189.5 1857.34   199.6  1854.8   208.5 1853.59
  216.88 1854.81   226.6 1856.04  237.771856.329  267.771856.464   292.1 1856.23
   363.6 1857.73   370.5 1858.94   379.8 1861.74   384.5 1860.95   398.6 1855.54
   403.2 1855.08   412.5 1858.72   435.9 1862.47   445.2 1866.01   456.8    1866
#Mann= 5 ,-1,0
       0     .06       0   199.6    .045       0  216.88     .06       0
  237.77     .05       0  267.77      .1       0
Bank Sta=199.6,216.88
XS Rating Curve= 0 ,0
Exp/Cntr=0.3,0.1

Type RM Length L Ch R = 1 ,10      ,224.5,216.9,209.3
XS GIS Cut Line= 4
2200125.27410568674518.4454981142200216.16720552674512.271627182
2200278.86654835674514.6718808372200504.82853899674579.579319971
#Sta/Elev= 30
       0 1873.07     6.9 1872.34      101871.193    14.9 1868.51      23 1862.79
      31 1855.75      35 1854.12      55 1852.98    66.3 1853.42    75.1 1854.01
    91.1 1856.83   110.2 1854.51   119.1 1852.68   127.1 1853.55  129.28 1854.52
   135.1 1856.61   155.2 1858.66   180.2 1856.74     201 1857.56  213.851856.962
   249.9 1857.41     283  1856.2   296.7 1857.42   300.9 1856.78   305.7 1855.04
   318.6 1854.36   359.1  1862.5   367.5 1865.93   371.6 1866.86   388.9 1865.31
#Mann= 5 ,-1,0
       0      .1       0      10     .06       0   110.2    .045       0
  129.28     .05       0  213.85      .1       0
#XS Ineff= 2 , 0
           43.89 1857.82
Permanent Ineff=
       F       F
Bank Sta=110.2,129.28
XS Rating Curve= 0 ,0
Exp/Cntr=0.3,0.1
LCMann Table=0

Chan Stop Cuts=-1
Use User Specified Reach Order=0
Composite Channel Slope=5